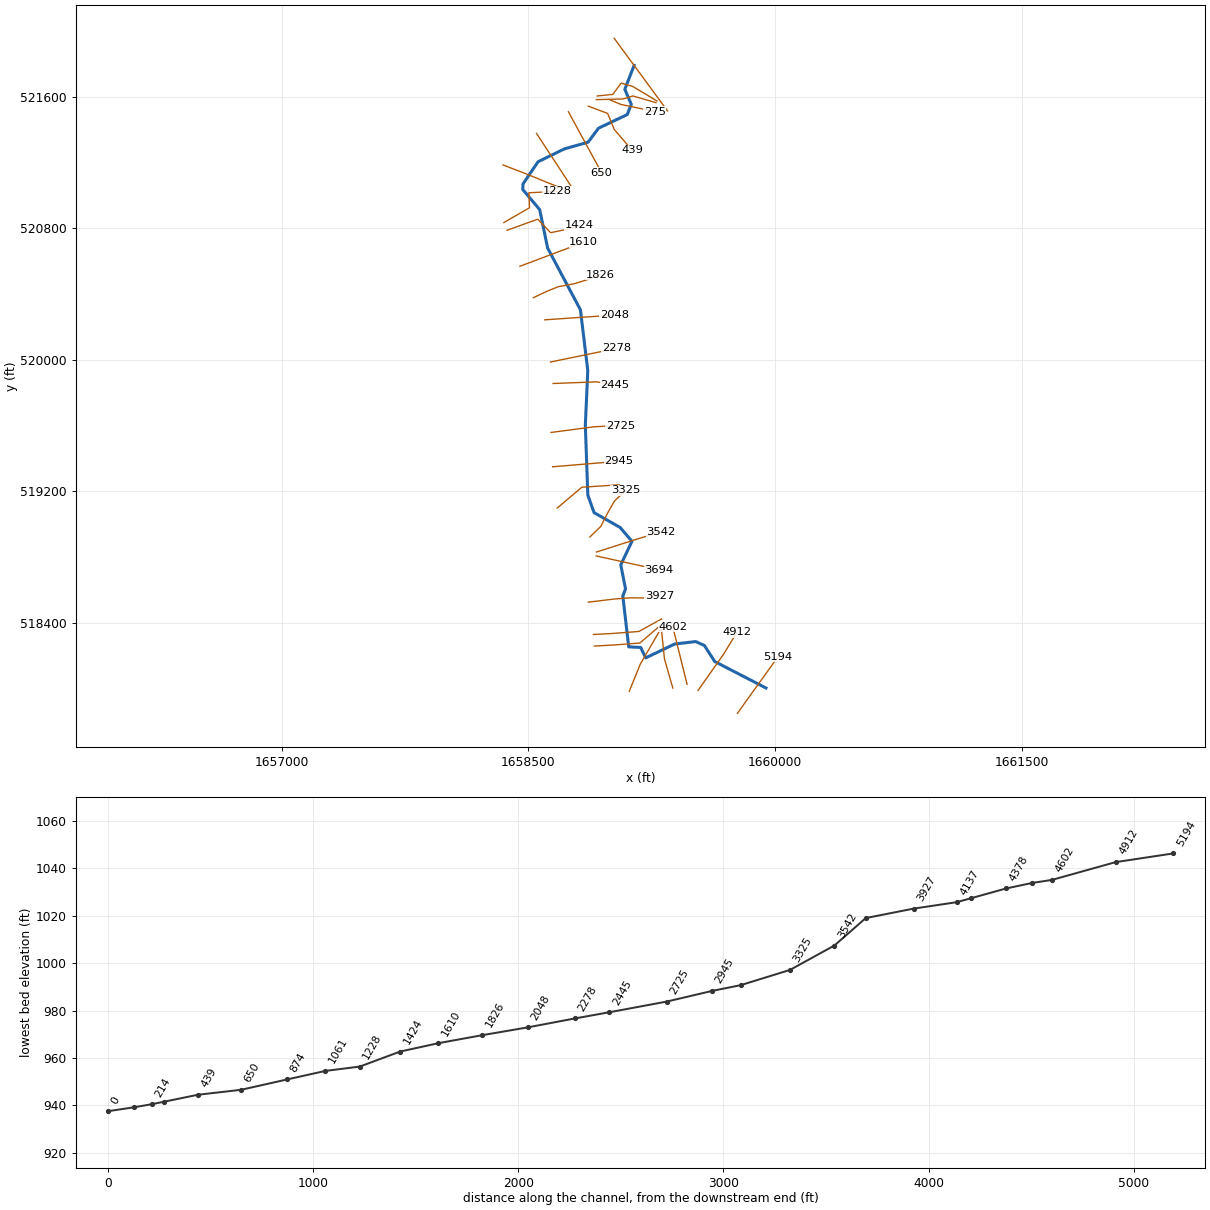
--- StullRnT1.prj (project) ---

Proj Title=StullRnT1
Current Plan=p01
Default Exp/Contr=0,0
English Units
Geom File=g01
Flow File=f01
Plan File=p01
BEGIN DESCRIPTION:
---------- MODELED AS PART OF WVEM CTP PROGRAM, 2025----------
Stream Name: Stull Run Tributary 1
Flood Zone: AFH
Marshall County, WV
HEC-RAS Version: RAS 6.6
Vertical Datum: NAVD88
Projection: NAD 1983 StatePlane West Virginia N FIPS 4701 (US Feet)
Terrain: 1-meter West Virginia FEMA R3 South Central (collected 2018-2019)
Land Use: 2024 NLCD
Hydrologic Method:
Duda et al., "Estimation of magnitude and frequency of floods for rural, unregulated streams in and near Virginia and West Virginia." September 8, 2025.
Additional Model Notes:
KWSEL/coincident peak boundary condition
END DESCRIPTION:
DSS Export Rating Curves= 0
DSS Export Rating Curve Sorted= 0
DSS Export Volume Flow Curves= 0
DXF OffsetX= 0
DXF OffsetY= 0
DXF ScaleX= 0
DXF ScaleY= 0

--- StullRnT1.p01 (plan) ---

Plan Title=Floodplain
Program Version=6.60
Short Identifier=Floodplain
Geom File=g01
Flow File=f01
Subcritical Flow
K Sum by GR= 0
Std Step Tol= 0.01
Critical Tol= 0.01
Num of Std Step Trials= 20
Max Error Tol= 0.3
Flow Tol Ratio= 0.001
Split Flow NTrial= 30
Split Flow Tol= 0.02
Split Flow Ratio= 0.02
Log Output Level= 0
Friction Slope Method= 1
Unsteady Friction Slope Method= 2
Unsteady Bridges Friction Slope Method= 1
Parabolic Critical Depth
Global Vel Dist= 0 , 0 , 0
Global Log Level= 0
CheckData=False
Encroach Param=-1 ,0,0, 0
Flow Ratio Tolerance=0.1
Flow Ratio Min Ratio=0.5
Flow Ratio Max Ratio=4
Flow Ratio Max Iterations= 10
Mapping Interval=1HOUR
Computation Time Step Use Courant=        0
Computation Time Step Use Time Series=    0
Computation Time Step Count To Double=0
Computation Time Step Max Doubling=0
Computation Time Step Max Halving=0
Computation Time Step Residence Courant=0
Run HTab= 0
Run UNet= 0
Run Sediment= 0
Run PostProcess= 0
Run WQNet= 0
Run RASMapper=-1
UNET Theta= 0
UNET Theta Warmup= 0
UNET ZTol= 0
UNET ZSATol= 0
UNET MxIter= 0
UNET Max Iter WO Improvement= 0
UNET MaxInSteps= 0
UNET DtIC= 0
UNET DtMin= 0
UNET MaxCRTS= 0
UNET WFStab= 0
UNET SFStab= 0
UNET WFX= 1
UNET SFX= 1
UNET Gravity=32.17405
UNET 1D Methodology=Finite Difference
UNET DSS MLevel= 1
UNET Pardiso=0
UNET DZMax Abort= 0
UNET Use Existing IB Tables= 0
UNET Froude Reduction=False
UNET Froude Limit= 0
UNET Froude Power= 0
UNET D1 Cores= 0
UNET WindReference=Eulerian
UNET WindDragFormulation=Hsu (1988)
UNET D2 Coriolis=0
UNET D2 Cores= 0
UNET D2 Theta= 1
UNET D2 Theta Warmup= 1
UNET D2 Z Tol= 0.01
UNET D2 Volume Tol= 0.01
UNET D2 Max Iterations= 20
UNET D2 Advanced Convergence=0
UNET D2 WS Max Tol=0.15
UNET D2 WS RMS Tol=0.002
UNET D2 WS Stall Tol=1
UNET D2 Equation= 0
UNET D2 RampUpFraction=0.1
UNET D2 TimeSlices= 1
UNET D2 Turbulence Formulation=Non-Conservative (original)
UNET D2 Eddy Viscosity=0.3
UNET D2 Transverse Eddy Viscosity=0.1
UNET D2 Smagorinsky Mixing=0
UNET D2 BCVolumeCheck=0
UNET D2 Cores=0
UNET D2 SolverType=PARDISO (Direct)
UNET D2 Minimum Iterations= 3
UNET D2 Maximum Iterations= 30
UNET D2 Restart Number= 10
UNET D2 Relaxation Coeff=1.3
UNET D2 SOR Precondition Iterations= 10
UNET D2 ILUT Maximum Fill= 8
UNET D2 ILUT Tolerance=1E-08
UNET D2 Convergence Tolerance=0.00001
PS Theta= 1
PS WS Tol= 0.01
PS Volume Tol= 0.01
PS Max Iterations= 20
PS Equation= 0
PS Advance Time Step=-1
PS Target Courant=0.9
PS Time Slices= 1
PS Iterate With 2D=0
PS Project Initial WSE from DS=-1
PS Ramp Up Initial WSE from US=-1
PS Cores=0
UNET D1D2 MaxIter= 0
UNET D1D2 ZTol=0.01
UNET D1D2 QTol=0.1
UNET D1D2 MinQTol=1
Write IC File= 0
Write IC File at Fixed DateTime=0
Write IC File at Sim End=0
Echo Input=False
Echo Parameters=False
Echo Output=False
Write Detailed= 0
HDF Write Warmup=0
HDF Write Time Slices=0
HDF Flush=0
HDF Compression= 1
HDF Chunk Size= 1
HDF Spatial Parts= 1
HDF Use Max Rows=0
HDF Fixed Rows= 1
Calibration Method= 0
Calibration Iterations= 20
Calibration Max Change=0.05
Calibration Tolerance=0.2
Calibration Maximum=1.5
Calibration Minimum=0.5
Calibration Optimization Method= 1
WQ AD Non Conservative
WQ ULTIMATE=-1
WQ Max Comp Step=1HOUR
WQ Output Interval=15MIN
WQ Output Selected Increments= 0
WQ Create Restart=0
WQ Fixed Restart=0
WQ System Summary=0
WQ Write To DSS=0
Sorting and Armoring Iterations= 10
XS Update Threshold= 0.02
Bed Roughness Predictor= 0
Processes Affected by Predictor=Sediment Only
Hydraulics Update Threshold= 0.02
Energy Slope Method= 1
Volume Change Method= 1
Sediment Retention Method= 0
Sediment TS Multiplier= 1
Warm Up Method= 0
XS Weighting Method= 0
Number of US Weighted Cross Sections= 1
Number of DS Weighted Cross Sections= 1
Upstream XS Weight=0
Main XS Weight=1
Downstream XS Weight=0
Number of DS XS's Weighted with US Boundary= 1
Upstream Boundary Weight= 1
Weight of XSs Associated with US Boundary= 0
Number of US XS's Weighted with DS Boundary= 1
Downstream Boundary Weight= 0.5
Weight of XSs Associated with DS Boundary= 0.5
Percentile Method= 0
Sediment Output Level= 3
Mass or Volume Output= 0
Output Increment Type= 1
Profile and TS Output Increment= 1
Transport Output Increment 1
XS Output Flag= 0
XS Output Increment= 10
Read HDF5 Sediment Hotstart= 0
Sediment Hotstart Type= 0
Write Gradation File= 0
Read Gradation Hotstart= 0
Write HDF5 File= 1
Write Binary Output= 1
Write DSS Sediment File= 0
DSS Sediment Output Type= 1
SV Curve= 0
Specific Gage Flag= 0
Subcell Erosion Methods= 0
Subcell Deposition Methods= 0
Advection Scheme= 1
Matrix Solver= 0
Implicit Weighting Factor= 1
Maximum Outer Loop Convergence Iterations= 5
Convergence Maximum Absolute= 0.001
Convergence RMSE= 0.0001
Grain Fractions Max Abs Error= 0.001
Max Subgrid Regions= 1
Max Subgrid Length Scale= 3.402823E+38
Initial Layer Thickness= 3
Min Layer Thickness= 0.1
Max Layer Thickness= 6
Number of Layers= 5

--- StullRnT1.f01 (steady flow) ---

Flow Title=Flow
Program Version=6.60
Number of Profiles= 1
Profile Names=P100yr
River Rch & RM=StullRnT1,Main            ,5194
     893
River Rch & RM=StullRnT1,Main            ,3542
    1130
River Rch & RM=StullRnT1,Main            ,1061
    1130
River Rch & RM=StullRnT1,Main            ,0
    1610
Boundary for River Rch & Prof#=StullRnT1,Main            , 1
Up Type= 0
Dn Type= 1
Dn Known WS=941.8
DSS Import GetInterval= 0
DSS Import GetPeak= 0
DSS Import FillOption= 0

--- StullRnT1.g01 (geometry) ---

Geom Title=Geometry
Program Version=6.60

River Reach=StullRnT1       ,Main
Reach XY= 30
1659945.10717059518003.9768084071659633.38600001518164.881999999
1659569.95100001518262.879999995     1659517.088518286.465000004
1659388.99900001518271.4200000021659213.33300002518187.247000009
     1659182.836518250.6819999961659110.04800001518254.341000021
1659074.03600001518563.7639999991659090.58600003518606.908000022
1659061.65899999518753.280000016     1659129.712      518896.375
     1659057.999518980.1819999961658899.00600001519070.861000001
1658861.18900001519177.5259999931658846.09900002519602.307000011
1658860.98999999519933.887999997     1658816.316520304.187000021
     1658616.883520679.503000006     1658568.413520913.724000007
     1658465.314521036.4539999961658467.16100001521070.278000012
     1658558.199521204.6180000011658719.02599999521283.046000019
     1658862.976521323.7490000131658926.51199999521409.126000002
1659100.72100002521491.525000021     1659125.501521553.791000009
     1659086.366521645.5339999941659142.67219912521790.775073141

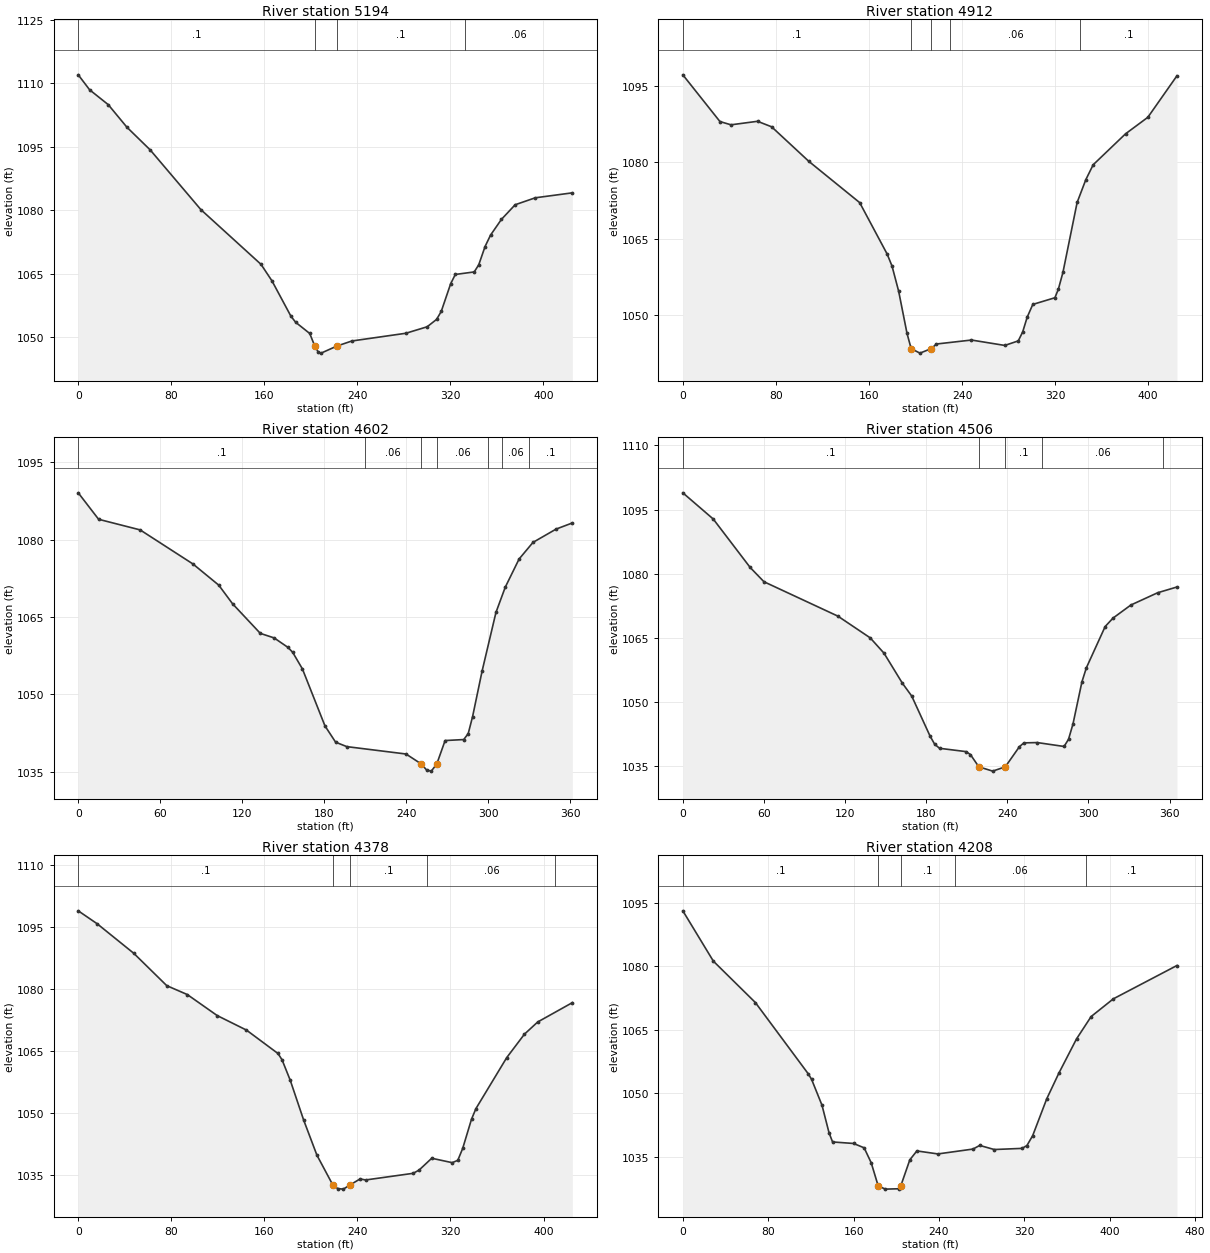
Type RM Length L Ch R = 1 ,5194    ,281.7,282.1,281.9
XS GIS Cut Line= 6
1659771.54394671517849.7331871291659821.87881979517921.327532132
1659865.65169813517982.2283289631659924.01673888518063.428953965
1659967.78994529518124.3297507961660018.97225763518195.285317545
#Sta/Elev= 30
       0 1111.96     9.8 1108.42    25.8 1104.92    41.8 1099.61    61.9 1094.23
   105.5 1080.13   157.2 1067.22   166.6 1063.33   182.9 1054.99     187 1053.54
   199.1  1050.9  203.461047.921   206.5 1046.47   208.9 1046.26  222.511047.937
   235.4 1049.13   281.8 1050.95   300.1 1052.48   308.2 1054.22   312.2 1056.09
   320.3 1062.62   324.3 1064.83   340.6 1065.43   344.5 1067.13   349.9 1071.42
   354.6 1074.11     364 1077.84   375.8 1081.29   393.1 1082.93     425  1084.1
#Mann= 4 ,-1,0
       0      .1       0  203.46    .045       0  222.51      .1       0
  332.52     .06       0
Bank Sta=203.46,222.51
XS Rating Curve= 0 ,0
Exp/Cntr(USF)=0,0
Exp/Cntr=0.3,0.1

Type RM Length L Ch R = 1 ,4912    ,304.5,310.1,314.8
XS GIS Cut Line= 3
1659531.38955142517988.9370046161659687.90842971518211.078573622
1659767.57764243518341.689336002
#Sta/Elev= 30
       0  1097.2    31.9 1088.03    41.4 1087.39    64.2 1088.08    76.3    1087
   108.4  1080.2     152 1072.12   175.6 1062.03   179.8 1059.67   185.5 1054.73
   192.7 1046.44  196.241043.461   203.8 1042.58  213.451043.459     218 1044.37
   248.1 1045.15   276.7 1044.09   288.3 1044.98   292.1 1046.74     296 1049.65
   300.8 1052.14   319.8 1053.45   322.8 1055.15   326.7 1058.42   338.9 1072.15
   346.4 1076.64   352.7 1079.55   380.5 1085.62   399.7 1088.87   424.7 1097.01
#Mann= 5 ,-1,0
       0      .1       0  196.24    .045       0  213.45      .1       0
     230     .06       0  341.74      .1       0
Bank Sta=196.24,213.45
XS Rating Curve= 0 ,0
Exp/Cntr(USF)=0,0
Exp/Cntr=0.3,0.1

Type RM Length L Ch R = 1 ,4602    ,99.2,96,93.9
XS GIS Cut Line= 2
1659464.91863681 518027.018573651659377.59357035518377.829460833
#Sta/Elev= 30
       0 1089.05    14.9 1083.92    45.3 1081.86    83.9 1075.26   102.8 1071.15
   112.9 1067.54   133.2  1061.8   143.3 1060.92   153.5 1059.07   156.9 1058.12
     164 1054.91   180.5 1043.86   188.3  1040.7   196.5 1039.84   239.8 1038.41
  250.951036.483   254.9  1035.3   258.3 1035.09  262.311036.482   268.4 1041.02
     282 1041.21   285.3 1042.36   288.5 1045.66   295.5 1054.54   305.6 1065.86
   312.4 1070.75   322.5 1076.21   332.7 1079.44   349.6 1082.02   361.5 1083.21
#Mann= 7 ,-1,0
       0      .1       0     210     .06       0  250.95    .045       0
  262.31     .06       0     300      .1       0     310     .06       0
     330      .1       0
Bank Sta=250.95,262.31
XS Rating Curve= 0 ,0
Exp/Cntr(USF)=0,0
Exp/Cntr=0.3,0.1

Type RM Length L Ch R = 1 ,4506    ,130.5,127.9,122.2
XS GIS Cut Line= 3
1659378.45332938518003.4162802321659327.28193998518181.633877784
1659308.75436796518360.733740671
#Sta/Elev= 30
       0 1098.92    22.5 1092.79    49.8 1081.46      60 1078.12   114.7 1070.07
   138.6 1064.99   148.8 1061.41   162.4 1054.38   169.3 1051.38   182.9 1041.99
   186.3  1040.1   189.9 1039.15   209.4 1038.38   212.7  1037.7  218.961034.817
   229.2 1033.81  238.531034.818     249 1039.54   252.3 1040.42   262.2 1040.49
     282 1039.58   285.3 1041.26   288.6 1044.85   295.2 1054.68   298.5 1057.99
   312.4 1067.64   318.2 1069.61   331.4 1072.67   351.2 1075.54   365.5 1076.89
#Mann= 5 ,-1,0
       0      .1       0  218.96    .045       0  238.53      .1       0
  265.42     .06       0  355.42      .1       0
Bank Sta=218.96,238.53
XS Rating Curve= 0 ,0
Exp/Cntr(USF)=0,0
Exp/Cntr=0.3,0.1

Type RM Length L Ch R = 1 ,4378    ,181.5,169.7,165.6
XS GIS Cut Line= 3
 1659113.4130231517984.1085234371659181.22885028518150.987377616
 1659304.2800545518362.507163379
#Sta/Elev= 30
       0 1098.89    16.2 1095.77    47.7 1088.61    76.1 1080.76    93.8  1078.6
   119.5 1073.51   144.6    1070   171.7 1064.33   175.2 1062.81   182.3 1057.81
   193.8 1048.19   205.2 1039.69  218.771032.526   223.1  1031.6   227.9 1031.47
   233.91032.526   242.3 1033.94   247.1 1033.69   287.9  1035.3     293 1036.08
   303.9 1038.95   321.5 1037.88   326.3 1038.45   330.5 1041.32   338.1 1048.41
   341.9 1050.98   368.4 1063.34   383.6 1069.01     395 1071.96   424.8 1076.65
#Mann= 5 ,-1,0
       0      .1       0  218.77    .045       0   233.9      .1       0
  300.13     .06       0  410.13      .1       0
Bank Sta=218.77,233.9
XS Rating Curve= 0 ,0
Exp/Cntr(USF)=0,0
Exp/Cntr=0.3,0.1

Type RM Length L Ch R = 1 ,4208    ,72.1,71.1,72
XS GIS Cut Line= 4
1658901.04784228 518259.218941441659025.83909531518265.898838166
1659177.78479179518277.662375958 1659318.7141669 518398.54209134
#Sta/Elev= 30
       0 1093.09    28.6 1081.21      68 1071.43   117.3 1054.68   120.6 1053.33
   130.4 1047.19     137 1040.68   140.3 1038.52     160 1038.16   169.9 1037.13
   176.5 1033.61  183.031028.156   189.7 1027.38   202.8 1027.47  204.241028.161
   212.7  1034.3   219.3  1036.4     239 1035.69   271.9 1036.84   278.2  1037.7
   291.8 1036.73   317.8    1037   322.4 1037.66   327.8    1040     341 1048.71
   352.3 1054.74   368.9 1062.85   382.6 1068.13   403.4 1072.31     463 1080.18
#Mann= 5 ,-1,0
       0      .1       0  183.03    .045       0  204.24      .1       0
  254.97     .06       0  377.37      .1       0
Bank Sta=183.03,204.24
XS Rating Curve= 0 ,0
Exp/Cntr(USF)=0,0
Exp/Cntr=0.3,0.1

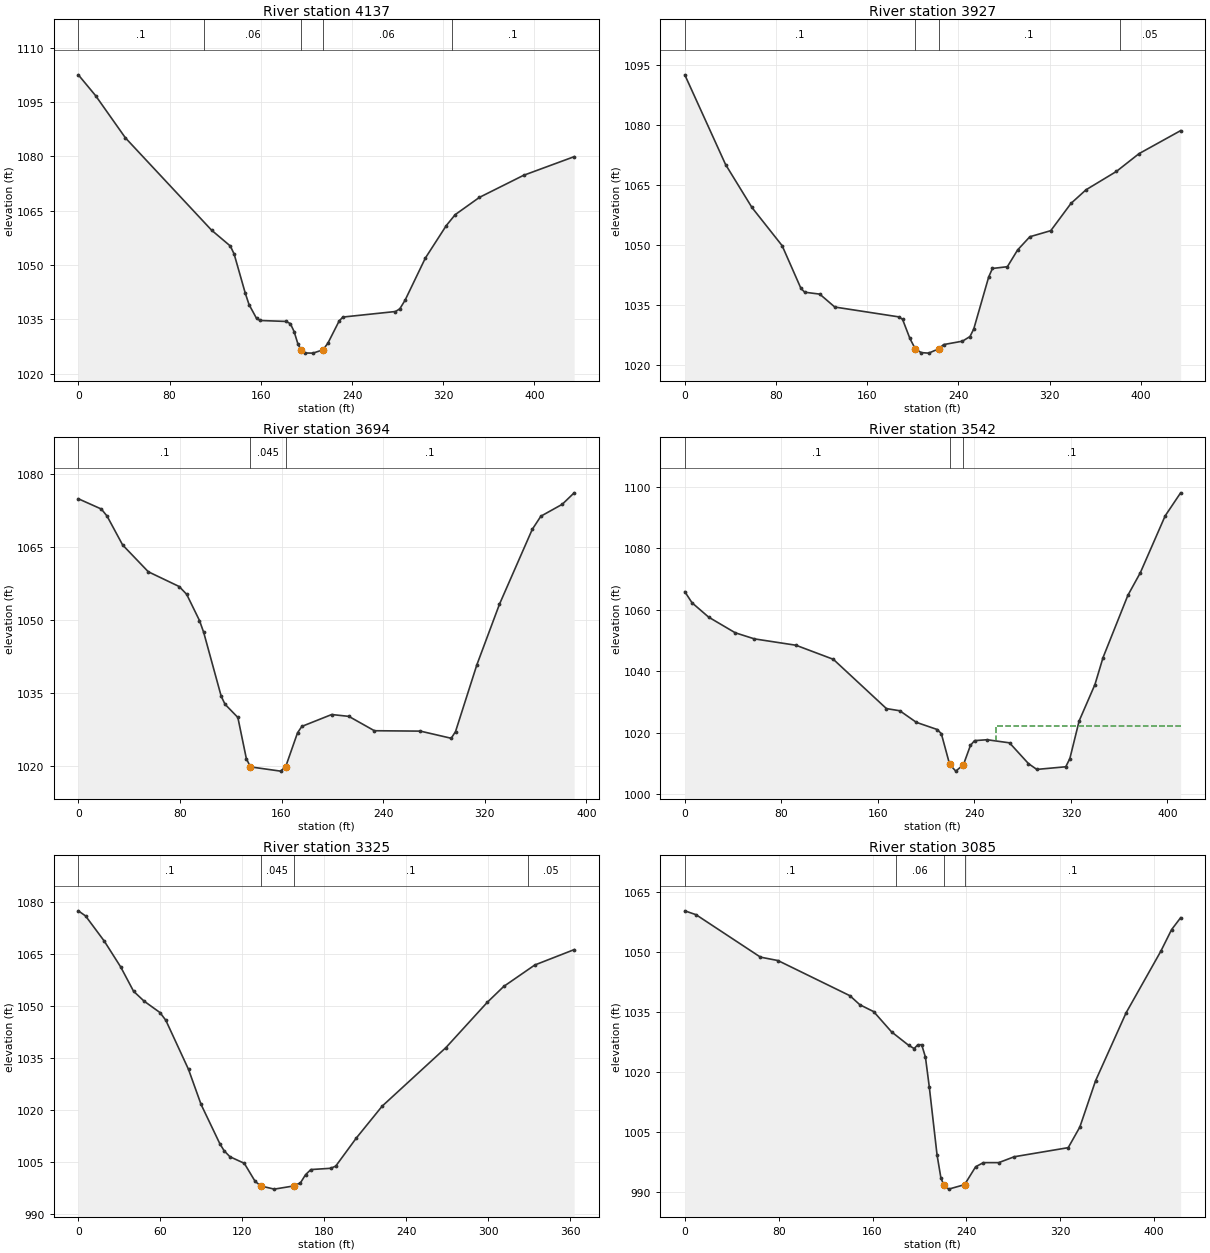
Type RM Length L Ch R = 1 ,4137    ,209.7,209.7,209.5
XS GIS Cut Line= 4
1658894.93937087518329.557358193 1659019.7306239 518336.23725492
1659171.67632038518348.0007927121659309.66481104518423.786946557
#Sta/Elev= 30
       0 1102.53    15.2 1096.76    41.3 1085.12   116.8 1059.65   133.3 1055.26
   136.6 1053.07   146.4 1042.24   149.7 1039.09   156.3 1035.27   159.6  1034.7
     182 1034.44   185.9 1033.85   189.2 1031.66   192.5 1028.29  195.191026.591
   199.1 1025.73   205.7 1025.69  214.481026.588   218.8 1028.41   228.7 1034.56
     232 1035.65   278.1 1037.18   281.9 1037.92   286.5 1040.28   304.3 1051.93
   322.7 1060.92   330.5 1063.93   351.7 1068.69   390.4 1074.78   434.8 1079.93
#Mann= 5 ,-1,0
       0      .1       0     110     .06       0  195.19    .045       0
  214.48     .06       0  327.37      .1       0
Bank Sta=195.19,214.48
XS Rating Curve= 0 ,0
Exp/Cntr(USF)=0,0
Exp/Cntr=0.3,0.1

Type RM Length L Ch R = 1 ,3927    ,236.5,233,229.3
XS GIS Cut Line= 6
1658864.51415984518526.2404760871658951.39095458518536.666308254
1659025.85635684518545.6026420891659126.46737608518552.811617166
  1659204.494451518551.7210681741659296.90863626518566.351944417
#Sta/Elev= 30
       0  1092.6    35.8 1070.15    58.9 1059.42    85.4 1049.86   101.9 1039.17
   105.2 1038.22   118.4 1037.74   131.6 1034.51   187.7 1032.05     191 1031.46
   197.5 1026.64  202.211024.043   207.4 1023.11     214 1022.98  222.641024.044
   227.1 1025.12   243.6 1025.97   250.2 1027.13   253.5 1029.01   266.6 1042.02
   269.9 1044.16     283  1044.6     292  1048.8   302.7 1052.09   321.1 1053.62
   338.8 1060.43     352 1063.84   378.6 1068.42   398.5 1072.88     435 1078.64
#Mann= 4 ,-1,0
       0      .1       0  202.21    .045       0  222.64      .1       0
   381.4     .05       0
Bank Sta=202.21,222.64
XS Rating Curve= 0 ,0
Exp/Cntr(USF)=0,0
Exp/Cntr=0.3,0.1

Type RM Length L Ch R = 1 ,3694    ,153.4,152.8,153.6
XS GIS Cut Line= 2
1658911.90705336518807.4572631881659293.15470676518723.246971846
#Sta/Elev= 30
       0 1074.96    18.1 1072.85    22.6 1071.41    34.9 1065.46    55.1 1059.96
    79.4 1056.93    85.3 1055.33    95.4 1049.94    98.7 1047.51   112.5 1034.38
   115.5 1032.74   125.6 1030.03   132.3 1021.56   135.51019.873   159.2    1019
   163.2 1019.87   172.6 1026.88     176 1028.19   199.5 1030.63     213 1030.25
   233.1  1027.3   269.3 1027.22   293.6 1025.75     297 1027.13   313.8 1040.85
   331.6  1053.3   357.4 1068.67   364.2 1071.38     381 1073.82   390.4 1076.18
#Mann= 3 ,-1,0
       0      .1       0   135.5    .045       0   163.2      .1       0
Bank Sta=135.5,163.2
XS Rating Curve= 0 ,0
Exp/Cntr(USF)=0,0
Exp/Cntr=0.3,0.1

Type RM Length L Ch R = 1 ,3542    ,211.1,216.7,222.6
XS GIS Cut Line= 3
1658913.99284337518831.3028018421659151.90059227518907.040379327
1659305.91471082518954.594480851
#Sta/Elev= 30
       0 1065.92       6 1062.29    19.8 1057.61    41.8 1052.52    57.7 1050.53
    92.1 1048.46   123.1 1043.87   167.1 1027.81   178.2  1027.1   191.9 1023.33
   209.2 1020.99   212.6 1019.63   219.5  1009.6   224.6 1007.43  230.91 1009.53
   236.7 1015.79   240.1 1017.37   250.5 1017.66   269.1 1016.65   284.8 1009.88
   291.7 1007.99   315.7 1008.85   319.1 1011.52   326.8 1023.79   339.9 1035.66
   346.6 1044.44   367.2 1064.74   377.5 1072.09   398.1 1090.63   410.9 1098.13
#Mann= 3 ,-1,0
       0      .1       0   219.5    .045       0  230.91      .1       0
#XS Ineff= 2 , 0
                          257.76         1022.07
Permanent Ineff=
       F       F
Bank Sta=219.5,230.91
XS Rating Curve= 0 ,0
Exp/Cntr(USF)=0,0
Exp/Cntr=0.3,0.1

Type RM Length L Ch R = 1 ,3325    ,248.5,240,226
XS GIS Cut Line= 5
1658873.28081849518922.1297398061658940.08749951518986.785158679
1658985.75866801519075.7472510931659023.54500976519141.588982925
1659091.53535934519206.186950833
#Sta/Elev= 30
       0 1077.53     5.3 1076.05      19 1068.77      31 1061.31    40.4  1054.3
    48.1 1051.44    59.7 1048.15      64 1045.91    80.6 1031.72    89.8 1021.58
   103.5 1010.26   106.7 1008.19   110.9 1006.49   121.4 1004.59   129.3  999.39
  133.53998.0406   143.3  997.13  157.46998.0406   162.5  998.96   166.2 1001.29
   170.1 1002.78   184.6 1003.15   188.3 1003.78   203.3 1011.87   222.3 1021.12
   268.9 1038.02   299.1 1051.08   311.2 1055.69   333.9 1061.88   362.7 1066.32
#Mann= 4 ,-1,0
       0      .1       0  133.53    .045       0  157.46      .1       0
  328.88     .05       0
Bank Sta=133.53,157.46
XS Rating Curve= 0 ,0
Exp/Cntr(USF)=0,0
Exp/Cntr=0.3,0.1

Type RM Length L Ch R = 1 ,3085    ,139.5,140.1,140.3
XS GIS Cut Line= 3
1658675.61485452519098.8299282771658824.83750985519225.179037896
1659051.41372449519240.074940975
#Sta/Elev= 30
       0 1060.24     9.6 1059.27    64.5 1048.67    79.4 1047.82   140.7 1039.04
   149.2 1036.78     161 1035.06   176.2 1030.01   190.9 1026.62   195.5 1025.84
   198.6 1026.77   201.9  1026.8   205.1 1023.69   208.4 1016.22     215  999.26
   218.3  993.49  220.68991.8424   224.9  990.72  238.45991.8395   247.9  996.31
   254.5  997.34   267.6  997.34   280.8  998.81   326.8 1001.08   336.7 1006.23
   350.1 1017.79   376.1 1034.75   405.7 1050.14   414.9 1055.55   422.6 1058.52
#Mann= 4 ,-1,0
       0      .1       0     180     .06       0  220.68    .045       0
  238.45      .1       0
Bank Sta=220.68,238.45
XS Rating Curve= 0 ,0
Exp/Cntr(USF)=0,0
Exp/Cntr=0.3,0.1

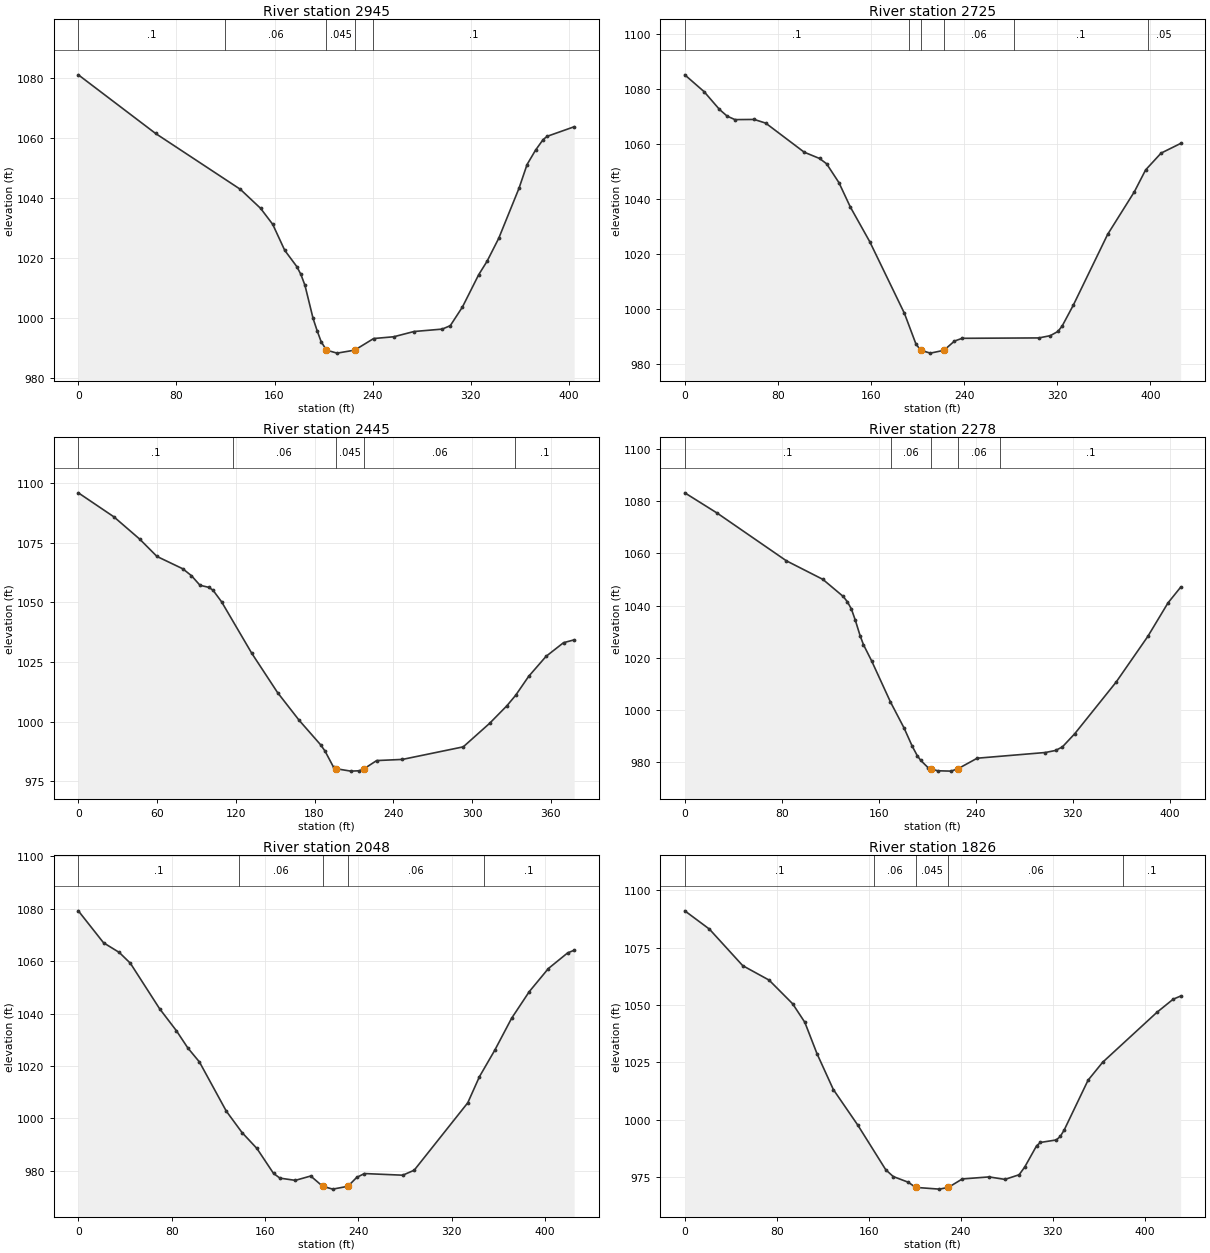
Type RM Length L Ch R = 1 ,2945    ,219.2,219.7,220.1
XS GIS Cut Line= 2
1658646.96991676519349.5944299431659049.87108614519382.924453687
#Sta/Elev= 30
       0 1080.97      63 1061.44   132.1 1042.84   148.6 1036.51   158.5 1031.18
   168.3 1022.52   178.2 1017.07   181.5 1014.47   184.8 1010.85   191.4  999.86
   194.7  995.77     198  992.09  202.33989.2712     211  988.28  225.32989.2707
   240.8  993.14   257.2  993.73   273.7  995.48   296.7  996.28   303.3  997.43
   313.2 1003.64   326.4 1014.36   333.3 1018.89   342.8 1026.53   359.3 1043.16
   365.9 1051.09   372.8 1055.88     379 1059.41   382.3 1060.49   404.3 1063.67
#Mann= 5 ,-1,0
       0      .1       0     120     .06       0  202.33    .045       0
  225.32     .06       0     240      .1       0
Bank Sta=202.33,225.32
XS Rating Curve= 0 ,0
Exp/Cntr(USF)=0,0
Exp/Cntr=0.3,0.1

Type RM Length L Ch R = 1 ,2725    ,279.9,279.6,278.2
XS GIS Cut Line= 6
1658637.54578176519558.3890023381658724.29823293519569.803021505
1658798.65733618519579.5867945851658897.80280717519592.631387919
1658972.87942867519596.9620879291659061.13778234519596.567403674
#Sta/Elev= 30
       0 1085.04    16.6 1078.91    29.8 1072.45    36.4 1070.01    43.1 1068.75
    59.6 1068.81    69.5 1067.48   102.6  1056.9   115.8 1054.61   121.8  1052.7
   132.4 1045.85   142.2 1036.98   158.9 1024.35   188.7  998.28   198.6  987.12
  202.78984.8287     211  983.81  222.61984.8289   231.7   988.2   238.3   989.2
   304.2  989.34     314  990.16   320.6   991.7   324.3  993.73   333.8 1001.26
   363.3 1027.01   386.3 1042.54   395.9 1050.44   409.2 1056.56     426 1060.08
#Mann= 6 ,-1,0
       0      .1       0   192.5     .06       0  202.78    .045       0
  222.61     .06       0   282.5      .1       0   397.7     .05       0
Bank Sta=202.78,222.61
XS Rating Curve= 0 ,0
Exp/Cntr(USF)=0,0
Exp/Cntr=0.3,0.1

Type RM Length L Ch R = 1 ,2445    ,165.4,167.8,169.2
XS GIS Cut Line= 5
1658649.91739435519856.0562374771658737.35258694519859.419419724
1658812.29731893519862.3016318111658912.22330018519866.144471902
1659026.18493037519848.451396124
#Sta/Elev= 30
       0 1095.88    27.1 1085.82    46.8 1076.47    59.9 1069.24    79.6 1064.06
    86.2 1061.17    92.7 1057.16    99.3 1056.31   102.6 1055.11   109.1 1050.28
   132.1 1028.72   151.8 1012.22   168.2 1000.64   184.6  990.35   187.9  987.77
   194.5  980.93  196.08 980.348   207.6  979.31   214.2  979.46  217.86980.3486
   227.3  983.73     247  984.22   293.3  989.48   313.3  999.29   326.5 1006.66
   333.2 1011.06   343.1 1018.98   356.4 1027.39   369.7 1033.11   377.8 1034.29
#Mann= 5 ,-1,0
       0      .1       0   117.5     .06       0  196.08    .045       0
  217.86     .06       0   332.5      .1       0
Bank Sta=196.08,217.86
XS Rating Curve= 0 ,0
Exp/Cntr(USF)=0,0
Exp/Cntr=0.3,0.1

Type RM Length L Ch R = 1 ,2278    ,231.7,230,228.7
XS GIS Cut Line= 2
1658634.25121891519986.8430210371659034.84140534520069.188622824
#Sta/Elev= 30
       0  1083.1    26.8 1075.32    83.8 1057.11   113.9 1050.01   130.7 1043.47
     134 1041.51   137.4 1038.72   140.7 1034.34   144.6  1028.5   147.4 1025.02
   154.1 1018.86   169.6 1003.19   180.9  993.16   187.6  986.23   191.8  982.58
   194.6  980.81     201  977.88  202.95977.5973   208.5  976.84   219.6   976.7
   225.3977.5981   241.2  981.64   297.4  983.82   305.8   984.6   311.5  985.97
   321.6  990.97   355.8 1010.74   381.9 1028.18   398.6 1041.03     409 1047.01
#Mann= 5 ,-1,0
       0      .1       0     170     .06       0  202.95    .045       0
   225.3     .06       0     260      .1       0
Bank Sta=202.95,225.3
XS Rating Curve= 0 ,0
Exp/Cntr(USF)=0,0
Exp/Cntr=0.3,0.1

Type RM Length L Ch R = 1 ,2048    ,219.2,221.4,219.7
XS GIS Cut Line= 6
1658599.66360253520243.353405655 1658686.9534542  520249.4154014
1658761.77351452520254.6115852451658861.53512603 520261.51380241
1658936.41030437520265.9107752451659023.78086454520270.802497745
#Sta/Elev= 30
       0 1079.22    21.6 1067.02    35.1 1063.32    44.6  1059.2    69.6 1041.87
    84.1 1033.41    93.9 1026.82   103.8  1021.5   126.8 1002.74   140.3  994.55
   153.1  988.45   167.3  978.94   172.8  977.13     186  976.28   199.2  977.94
  209.42974.0154   218.1  972.93  231.08974.0154   238.6   977.4   245.2  978.88
   278.1  978.25   287.9  980.16   333.8  1005.9   343.8 1015.87   356.9 1025.95
   371.4  1038.2   386.5 1048.35   402.9 1057.18   419.4 1063.15     425 1064.16
#Mann= 5 ,-1,0
       0      .1       0   137.5     .06       0  209.42    .045       0
  231.08     .06       0   347.5      .1       0
Bank Sta=209.42,231.08
XS Rating Curve= 0 ,0
Exp/Cntr(USF)=0,0
Exp/Cntr=0.3,0.1

Type RM Length L Ch R = 1 ,1826    ,211.7,216.4,217.8
XS GIS Cut Line= 6
1658529.67427833520377.9221401661658609.65640184520415.564125255
1658679.94202243520444.3268630061658778.58716634520462.987586841
1658852.07061517 520485.488854171658935.58652426520518.188591927
#Sta/Elev= 30
       0    1091    21.4 1083.03    50.4 1067.09    73.3  1060.8    93.8 1050.48
   104.4  1042.4     115 1028.71   129.2 1013.09   150.5  997.55   174.8   978.1
   181.3  975.14   194.3  972.67  200.86970.4048   221.4  969.65  229.25970.4031
   241.4  974.09   264.7  974.98   278.5  973.89   290.8  975.92   295.7  979.29
     306  988.54   309.4  990.01   323.1  991.09   326.6  992.61     330  995.41
   350.8 1017.16   363.5 1024.98   410.7 1046.75   424.8 1052.46   431.3 1053.84
#Mann= 5 ,-1,0
       0      .1       0  164.34     .06       0  200.86    .045       0
  229.25     .06       0  381.59      .1       0
Bank Sta=200.86,229.25
XS Rating Curve= 0 ,0
Exp/Cntr(USF)=0,0
Exp/Cntr=0.3,0.1

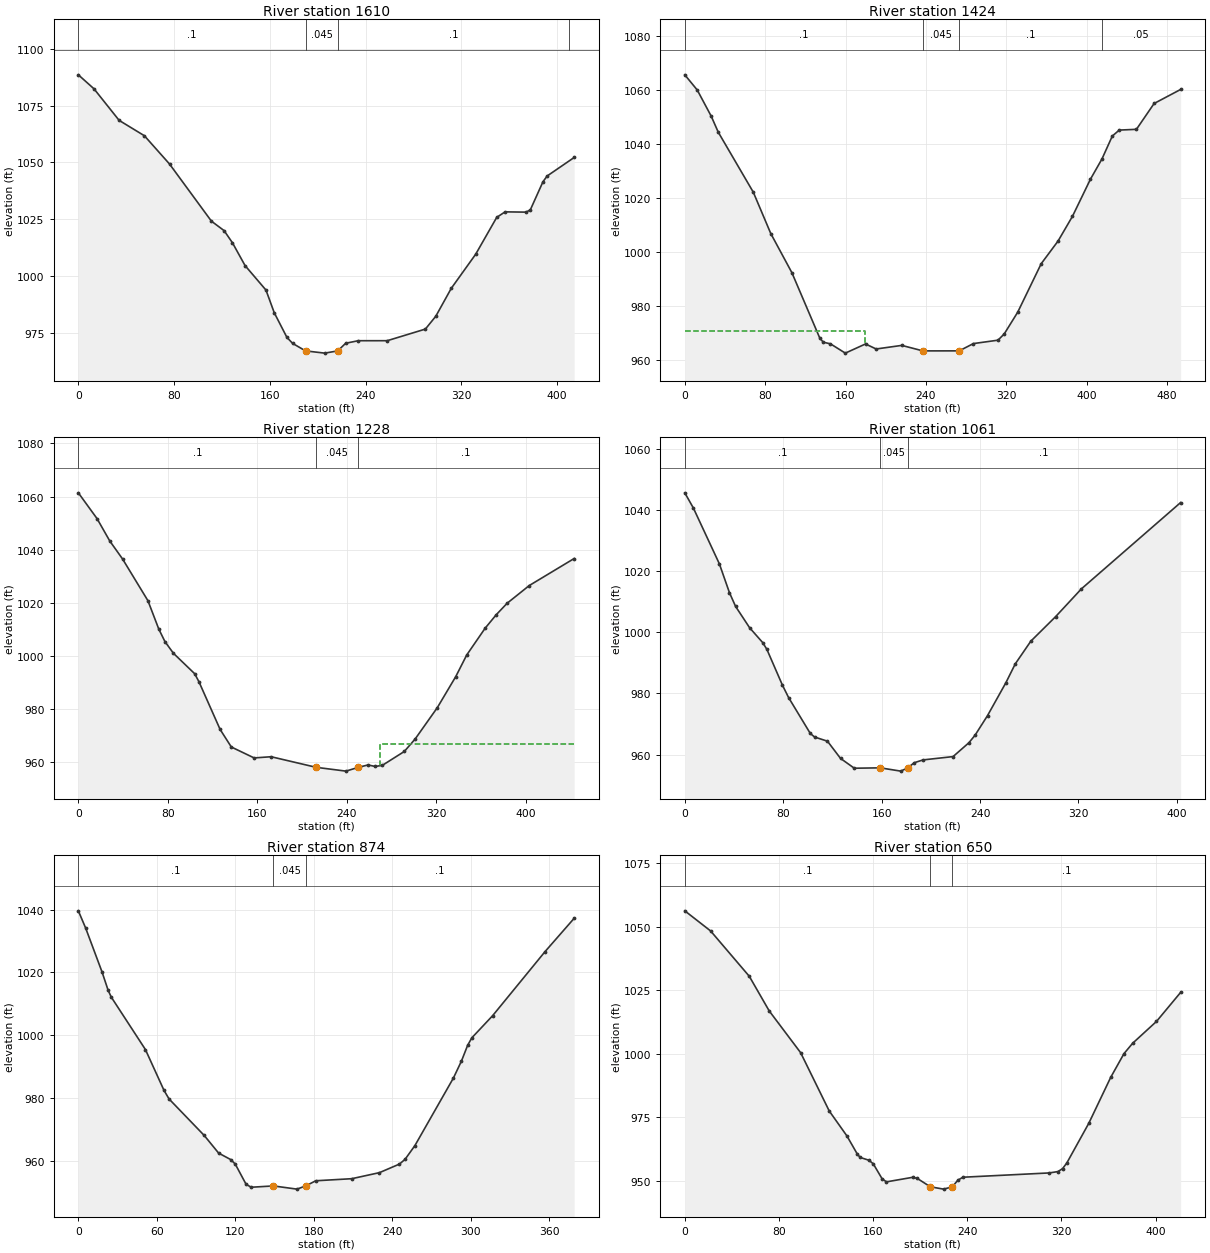
Type RM Length L Ch R = 1 ,1610    ,200,185.3,165.1
XS GIS Cut Line= 2
 1658448.1693871520568.9593270171658835.93044765520714.914332957
#Sta/Elev= 30
       0 1088.48    13.1 1082.33    34.1 1068.47    55.2 1061.72    76.2  1049.3
   111.2  1024.2   121.8 1020.04   128.8 1014.68   139.3  1004.7   156.8  993.92
   163.7  983.98   174.3  973.13   179.1  970.49  189.87967.2082   205.9  966.23
  216.72967.2064   223.4  970.57   233.9  971.68   258.1  971.69     290   976.8
   298.7  982.44   311.6  994.68     332 1009.66   349.6 1025.86   356.6 1028.29
   374.2 1028.16   377.7 1029.19   388.2 1041.47   391.7 1044.03   414.3 1052.17
#Mann= 4 ,-1,0
       0      .1       0  189.87    .045       0  216.72      .1       0
     410     .05       0
Bank Sta=189.87,216.72
XS Rating Curve= 0 ,0
Exp/Cntr(USF)=0,0
Exp/Cntr=0.3,0.1

Type RM Length L Ch R = 1 ,1424    ,156.5,196,228.4
XS GIS Cut Line= 5
 1658370.0662596 520787.96121357 1658556.4748305 520855.55524812
1658634.80246534520773.3942539261658726.23205711520792.230482139
1658811.00386919520817.461730875
#Sta/Elev= 30
       0  1065.6    12.4 1059.98    26.3 1050.31    33.3  1044.4    68.2  1022.2
    85.6 1006.92   106.6  992.46   134.5  968.17     138  966.73     145  966.15
   159.8  962.71   179.9   966.1   190.5  964.24     216  965.57  237.02 963.538
  273.21 963.548   287.3  966.24   311.8   967.5     318  969.81   331.4  977.83
   354.8  995.77   371.6 1004.16   385.9 1013.27   403.8    1027   415.3  1034.5
   425.6 1042.97   432.5 1045.17   449.6 1045.45   467.2    1055   493.6 1060.19
#Mann= 4 ,-1,0
       0      .1       0  237.02    .045       0  273.21      .1       0
  415.15     .05       0
#XS Ineff= 2 , 0
          179.78  971.06
Permanent Ineff=
       F       F
Bank Sta=237.02,273.21
XS Rating Curve= 0 ,0
Exp/Cntr(USF)=0,0
Exp/Cntr=0.3,0.1

Type RM Length L Ch R = 1 ,1228    ,201.5,167.4,145.6
XS GIS Cut Line= 4
1658350.80718201520834.8752945071658506.56235653520925.268274747
1658502.56970454521016.1551358781658674.44580187521024.611521177
#Sta/Elev= 30
       0 1061.39    16.7 1051.68    28.1 1043.22    39.5 1036.45    62.2 1020.69
    71.9 1009.99    77.4 1005.27      85 1000.85     104  993.14   107.8  990.11
   126.7  972.14   136.7  965.51   157.1  961.38   172.3  961.83  212.56957.8326
   239.2   956.4  250.23957.8322   258.9  958.73   265.2  958.17   271.6  958.56
   291.3  963.81   301.1  968.58   320.8  980.34   337.3  992.07   347.1 1000.22
   363.5 1010.29   373.4 1015.37   383.2 1019.73     403 1026.42   443.1 1036.61
#Mann= 3 ,-1,0
       0      .1       0  212.56    .045       0  250.23      .1       0
#XS Ineff= 2 , 0
                          269.31          966.79
Permanent Ineff=
       F       F
Bank Sta=212.56,250.23
XS Rating Curve= 0 ,0
Exp/Cntr(USF)=0,0
Exp/Cntr=0.3,0.1

Type RM Length L Ch R = 1 ,1061    ,193.7,187,180.2
XS GIS Cut Line= 3
1658345.57474629521185.3674774131658482.11020827521132.823675275
1658719.91012473521035.892123868
#Sta/Elev= 30
       0 1045.67       7 1040.67    28.1 1022.43    36.3 1012.99    41.3 1008.48
    52.7  1001.5    63.3  996.66    66.7  994.46    79.4  982.69    84.4  978.64
     102  966.92   105.5  965.74     116  964.36   126.6  958.74   137.8  955.52
  158.86955.6465   175.6  954.57  181.16955.6444   186.6  957.33   193.7  958.24
   218.1  959.33     231  963.87     236  966.34   246.1  972.74     261  983.48
   268.7   989.7   281.3   997.1   301.5 1005.15   322.4 1014.22   403.1 1042.49
#Mann= 3 ,-1,0
       0      .1       0  158.86    .045       0  181.16      .1       0
Bank Sta=158.86,181.16
XS Rating Curve= 0 ,0
Exp/Cntr(USF)=0,0
Exp/Cntr=0.3,0.1

Type RM Length L Ch R = 1 ,874     ,225.9,223.8,222.9
XS GIS Cut Line= 2
1658549.22744493521377.0459602041658757.12428276521059.866642416
#Sta/Elev= 30
       0 1039.58     5.6 1034.09    18.1 1020.15    22.8 1014.27    25.2  1012.1
    51.3  995.42    65.5  982.43    69.4  979.67    96.3  968.05   107.3  962.44
   116.5  960.39     120  958.96   128.3  952.51   132.2  951.57   149.2  951.99
   167.2  950.97  173.76 951.968   181.6  953.63   209.1  954.29   230.3  956.22
   245.6  958.95   249.9  960.47   257.4  964.83   286.9  986.38     293  991.74
   297.7  996.72   300.9  999.13   316.8 1006.17   356.9 1026.58   379.2  1037.2
#Mann= 3 ,-1,0
       0      .1       0   149.2    .045       0  173.76      .1       0
Bank Sta=149.2,173.76
XS Rating Curve= 0 ,0
Exp/Cntr(USF)=0,0
Exp/Cntr=0.3,0.1

Type RM Length L Ch R = 1 ,650     ,214.5,211.2,209.1
XS GIS Cut Line= 2
1658743.18943568  521508.77976841658944.64847533521138.906856086
#Sta/Elev= 30
       0  1056.3    21.9 1048.38    54.8 1030.49    71.7 1016.86    98.4 1000.39
   122.7  977.41   137.7  967.59   146.7   960.3   149.1  959.08   156.4     958
   160.1  956.59   167.6  950.69   171.3  949.47   193.7  951.28   197.5  950.82
  208.64947.5199   219.9  946.61  227.23947.5209   231.9   950.1   236.2   951.3
   309.5  952.99     317  953.53   320.9  954.69   324.5   956.9   343.2  972.57
   361.8  990.66   373.1 1000.03   380.5 1004.13   400.7 1012.71   421.2 1024.14
#Mann= 3 ,-1,0
       0      .1       0  208.64    .045       0  227.23      .1       0
Bank Sta=208.64,227.23
XS Rating Curve= 0 ,0
Exp/Cntr(USF)=0,0
Exp/Cntr=0.3,0.1

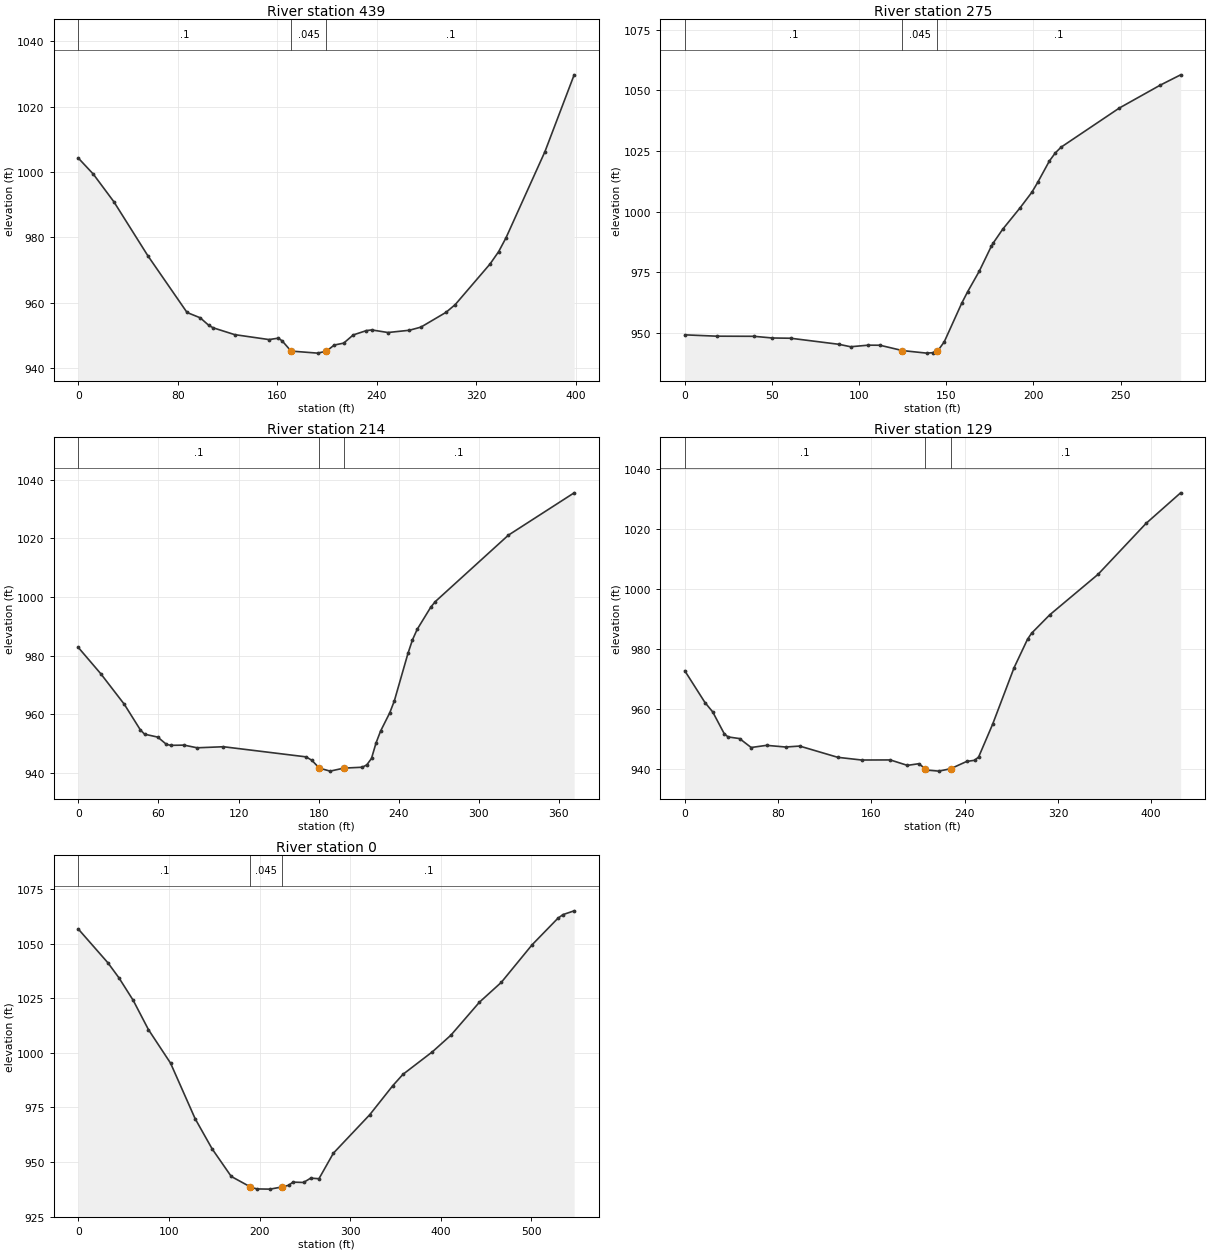
Type RM Length L Ch R = 1 ,439     ,150.4,163.7,172.3
XS GIS Cut Line= 4
1658864.17805621521543.0474421131658981.80854021521498.652100509
1659021.67254451521402.0194779631659130.95452853  521273.9533519
#Sta/Elev= 30
       0 1004.21    12.1  999.28    28.6  990.83    55.9  974.31    87.4  956.95
      98  955.32     105  952.97   108.5  952.25   125.7  950.17   153.3  948.66
   160.8  949.09   163.9  948.25     171  945.14   192.3  944.51   199.4  945.09
   205.7  946.98   213.3  947.57     221  950.08   231.6  951.41   235.9  951.61
   248.9  950.82   266.1  951.51   275.4  952.47   295.6     957     303  959.37
     331  971.81   337.9  975.58   343.8   979.8   375.1 1006.18   398.6  1029.7
#Mann= 3 ,-1,0
       0      .1       0     171    .045       0   199.4      .1       0
Bank Sta=171,199.4
XS Rating Curve= 0 ,0
Exp/Cntr(USF)=0,0
Exp/Cntr=0.3,0.1

Type RM Length L Ch R = 1 ,275     ,54.2,61,64.7
XS GIS Cut Line= 3
1658994.73723899521581.6676681451659060.97029937521553.829214399
1659269.00846523521510.157080345
#Sta/Elev= 30
       0  949.14    18.3  948.59    39.6  948.54    50.3  947.84    60.7  947.74
    88.4  945.24    95.1  944.23   105.2  944.88   111.9  944.86124.8532942.6494
   138.7   941.6   142.1  941.77144.7832942.6644   145.4  942.86   148.8  946.23
   158.8  962.12   162.2  966.88   168.9  975.39   175.8  985.65     177   987.1
   182.3  992.65   192.4  1001.6   199.1 1007.97   202.4 1011.99   209.1 1020.81
   212.5 1024.14   215.8 1026.52   249.3  1042.7   272.8 1052.15   284.4 1056.37
#Mann= 3 ,-1,0
       0      .1       0124.8532    .045       0144.7832      .1       0
Bank Sta=124.8532,144.7832
XS Rating Curve= 0 ,0
Exp/Cntr(USF)=0,0
Exp/Cntr=0.3,0.1

Type RM Length L Ch R = 1 ,214     ,90,84.6,78.4
XS GIS Cut Line= 4
1658912.75739212 521582.633054391659076.06885685521586.600056572
1659135.14990497521605.0737294611659275.46690783521564.266777623
#Sta/Elev= 30
       0  982.76    16.8   973.8    34.5  963.32    46.4  954.66    49.6  953.15
    59.5  952.15      66  949.67    69.3  949.34    79.2  949.41      89   948.5
   108.7  948.86   170.6   945.4   174.9  944.23  180.56  941.56   188.6  940.53
   198.9  941.56   212.7  941.86   216.1  942.68   219.6  944.87     223  950.16
   226.4  954.21   233.3  960.48   236.7  964.52   246.9  980.72   250.3  985.38
   253.8  988.94     264  996.54   267.4  998.44   322.1 1021.11   371.4 1035.58
#Mann= 3 ,-1,0
       0      .1       0  180.56    .045       0   198.9      .1       0
Bank Sta=180.56,198.9
XS Rating Curve= 0 ,0
Exp/Cntr(USF)=0,0
Exp/Cntr=0.3,0.1

Type RM Length L Ch R = 1 ,129     ,138.2,129.6,115.6
XS GIS Cut Line= 5
1658918.90380375521604.9943666971659012.83996972521614.249161374
1659064.20408018521683.1973817161659134.54051972521662.836833427
1659281.69175508521574.453544264
#Sta/Elev= 30
       0  972.77    17.3  962.17    23.9  959.06    33.8  951.77    37.1  950.68
      47  950.13    56.9  947.15    70.1  947.87    86.5  947.31    98.5  947.63
   131.2  943.87   151.7  942.97   176.2     943   190.9  941.18   200.7  941.74
  206.01  940.12   207.6  939.62   217.8  939.26     228  940.06   241.7  942.49
   248.6  942.89     252     944     264  954.94   282.4  973.82   293.9   983.3
   297.4  985.32     313  991.47   354.4 1004.98   395.5 1021.97   425.2  1032.2
#Mann= 3 ,-1,0
       0      .1       0  206.01    .045       0     228      .1       0
Bank Sta=206.01,228
XS Rating Curve= 0 ,0
Exp/Cntr(USF)=0,0
Exp/Cntr=0.3,0.1

Type RM Length L Ch R = 1 ,0       ,180.2,181.6,182.2
XS GIS Cut Line= 2
1659021.63794209521955.4491355491659345.77332619521514.444317706
#Sta/Elev= 30
       0 1056.77    32.6 1041.33    44.8 1034.44    60.6 1024.08    77.4 1010.68
   101.8  995.31   128.9  969.88   147.7  956.02   168.8  943.38     190  938.57
     197  937.66   211.7  937.57   225.2  938.59   232.1  939.33   236.9  940.77
   248.6  940.63   256.5  942.61   265.6  942.34   281.5  954.03   321.7  971.69
   347.2  985.04   358.3  990.17   390.9 1000.54   411.2 1008.11   442.8 1023.28
   466.9 1032.35   500.8 1049.53   529.3  1061.7   534.9 1063.39   547.3 1065.13
#Mann= 3 ,-1,0
       0      .1       0     190    .045       0   225.2      .1       0
Bank Sta=190,225.2
XS Rating Curve= 0 ,0
Exp/Cntr=0.3,0.1
LCMann Table=0

Chan Stop Cuts=-1
Use User Specified Reach Order=0
Composite Channel Slope=5